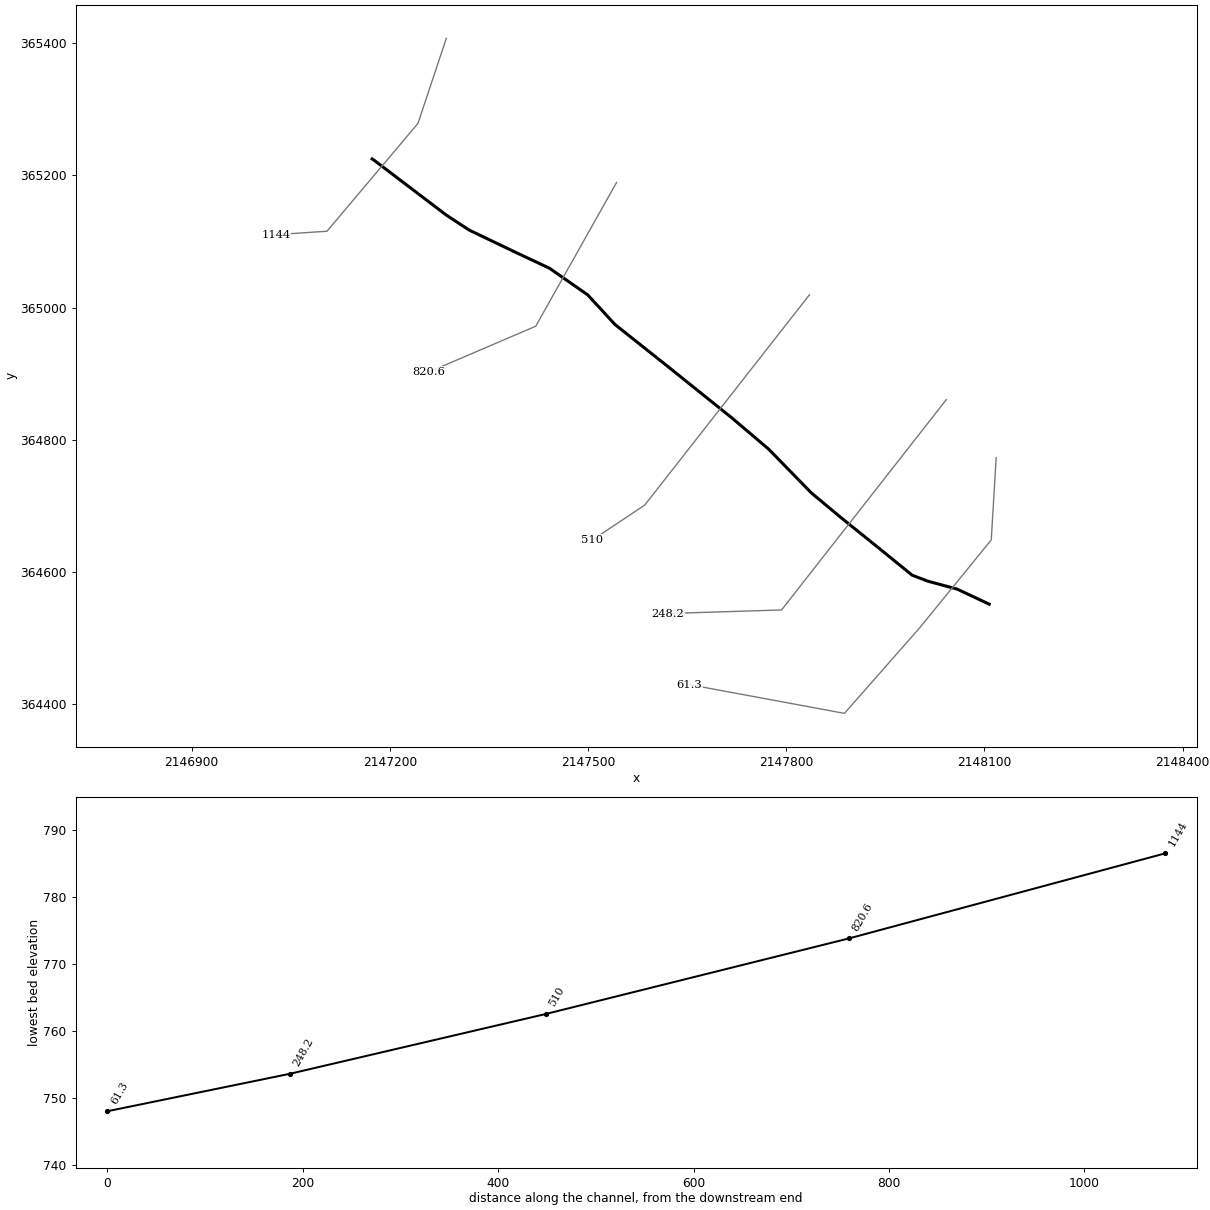
--- NP111.prj (project) ---

Proj Title=NP111
Current Plan=p01
Geom File=g01
Flow File=f01
Plan File=p01
DSS Export Rating Curves=0
DSS Export Rating Curve Sorted=0
DSS Export Volume Flow Curves=0
DXF OffsetX=0
DXF OffsetY=0
DXF ScaleX=0
DXF ScaleY=0

--- NP111.p01 (plan) ---

Plan Title=Floodplain
Program Version=4.00
Geom File=g01
Flow File=f01
K Sum by GR=0
Std Step Tol=0.01
Critical Tol=0.01
Num of Std Step Trials=20
Max Error Tol=0.3
Flow Tol Ratio=0.001
Split Flow NTrial=30
Split Flow Tol=0.02
Split Flow Ratio=0.02
Log Output Level=0
Friction Slope Method=1
Unsteady Friction Slope Method=2
Unsteady Bridges Friction Slope Method=1
Global Log Level=0
CheckData=False
Run HTab=0
Run UNet=0
Run PostProcess=0
UNET Theta=0
UNET Theta Warmup=0
UNET ZTol=0
UNET ZSATol=0
UNET MxIter=0
UNET MaxInSteps=0
UNET DtIC=0
UNET DtMin=0
UNET MaxCRTS=0
UNET WFStab=0
UNET SFStab=0
UNET WFX=0
UNET SFX=0
UNET DSS MLevel=0
UNET DZMax Abort=0
UNET Convert EG Bridges=0
UNET Use Existing IB Tables=0
UNET Froude Limit=0
UNET Froude Power=0
Write IC File=0
Echo Input=False
Echo Output=False
Write Detailed=0

--- NP111.f01 (steady flow) ---

Flow Title=NFF Regression Equation
Program Version=4.00
Number of Profiles=1
Profile Names=P100yr
River Rch & RM=NP111,Main      ,1144
      40
River Rch & RM=NP111,Main      ,820.6
      43
River Rch & RM=NP111,Main      ,248.2
      46
Boundary for River Rch & Prof#=NP111,Main      ,1
Up Type=0
Dn Type=3
Dn Slope=0.032882

--- NP111.g01 (geometry) ---

Geom Title=USGS 10m DEM
Program Version=4.00

River Reach=NP111     ,Main
Reach XY= 18
     2147173.265      365224.853     2147176.763      365222.521
     2147285.293      365140.060     2147320.224      365117.165
     2147390.994      365083.287     2147441.542      365059.524
     2147499.491      365019.206     2147540.869      364974.252
     2147618.126      364912.882     2147717.463      364833.166
     2147773.573      364785.508     2147837.950      364719.468
     2147883.014      364681.929     2147950.145      364627.815
     2147990.636      364594.824     2148014.542      364585.712
     2148058.621      364573.812     2148107.319      364550.954

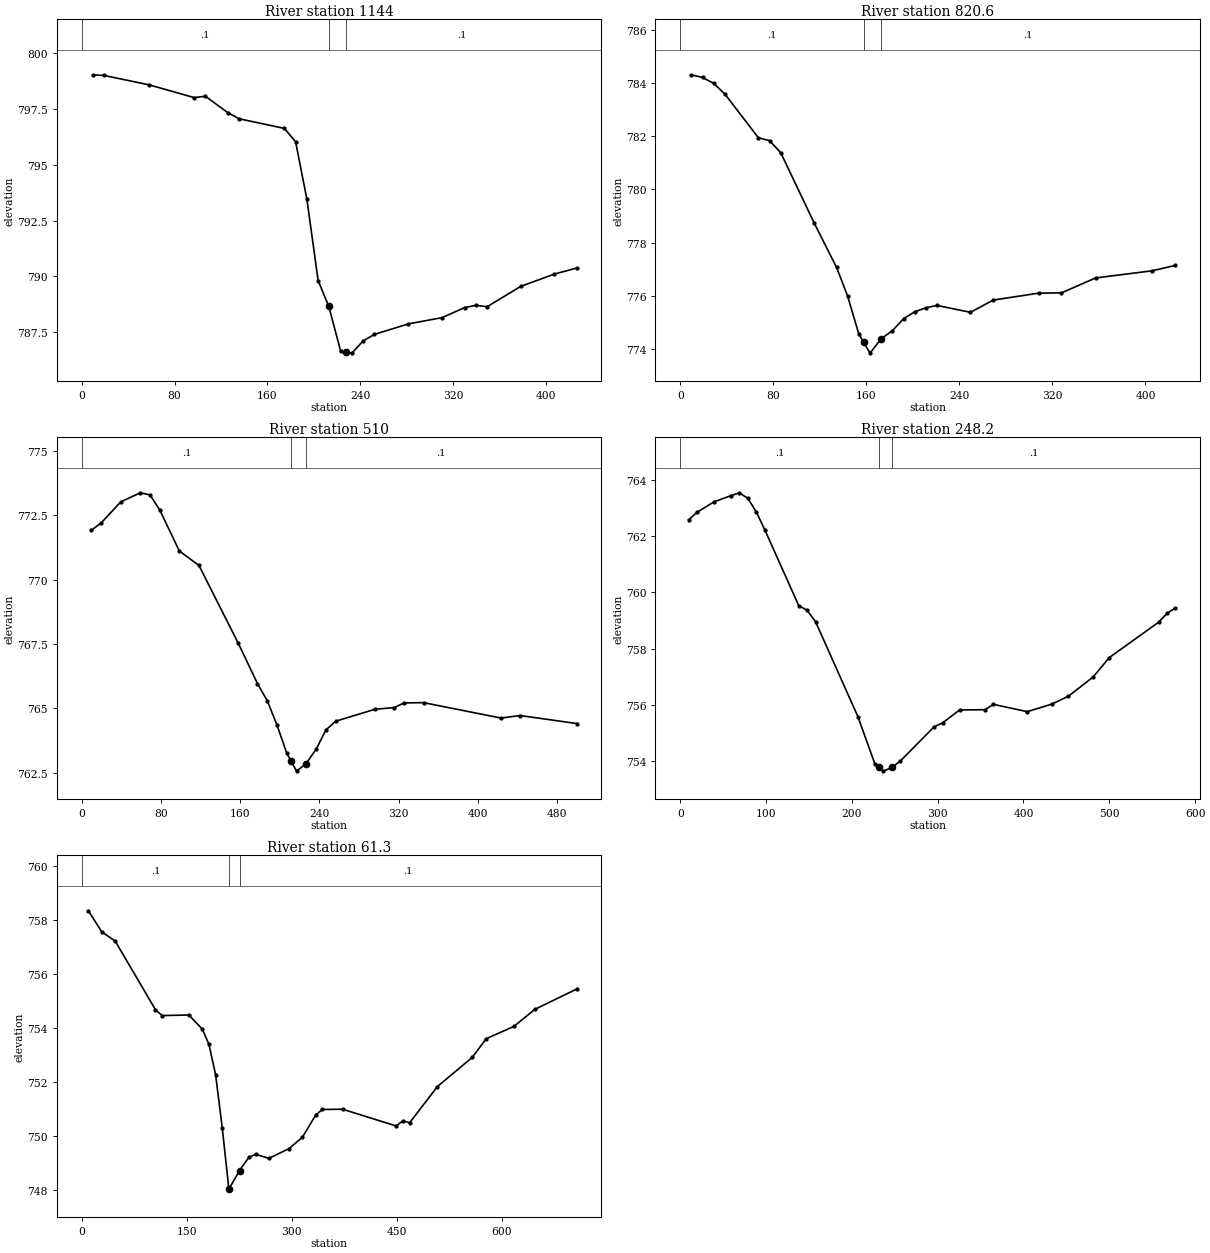
Type RM Length L Ch R = 1 ,1144,319.2,323.4,327.7
XS GIS Cut Line= 4
     2147285.527      365407.461     2147242.612      365278.716
     2147104.845      365115.444     2147028.036      365110.356
#Sta/Elev= 25
     9.7  799.03    19.4  799.00    58.2  798.58    96.9  798.01   106.6  798.07
   126.0  797.33   135.7  797.06   174.6  796.63   184.3  796.03   194.0  793.46
   203.7  789.81   212.9  788.65   223.1  786.65   227.9  786.61   232.8  786.56
   242.5  787.11   252.2  787.40   281.4  787.87   310.5  788.15   329.9  788.60
   339.6  788.70   349.3  788.64   378.2  789.55   407.1  790.10   426.3  790.37
#Mann= 3 , 0 , 0
       0     0.1       0   212.9   0.045       0   227.9     0.1       0
Bank Sta=   212.9,   227.9
Exp/Cntr=0.3,0.1

Type RM Length L Ch R = 1 ,820.6,314,310.5,307.1
XS GIS Cut Line= 3
     2147543.192      365189.216     2147420.875      364971.707
     2147259.118      364902.383
#Sta/Elev= 26
     9.6  784.30    19.2  784.20    28.8  783.98    38.4  783.58    67.2  781.94
    76.8  781.83    86.4  781.38   115.2  778.74   134.4  777.08   144.0  775.99
   153.6  774.57   157.8  774.26   163.2  773.86   172.8  774.40   182.4  774.70
   192.0  775.15   201.6  775.41   211.2  775.56   220.7  775.65   249.5  775.39
   269.1  775.85   308.2  776.11   327.8  776.12   357.1  776.68   406.0  776.95
   425.5  777.15
#Mann= 3 , 0 , 0
       0     0.1       0   157.8   0.045       0   172.8     0.1       0
Bank Sta=   157.8,   172.8
Exp/Cntr=0.3,0.1

Type RM Length L Ch R = 1 ,510,261.8,261.8,261.8
XS GIS Cut Line= 3
     2147835.307      365019.382     2147585.933      364701.011
     2147506.705      364648.193
#Sta/Elev= 26
     9.9  771.92    19.7  772.20    39.5  773.02    59.2  773.37    69.0  773.29
    78.9  772.70    98.6  771.11   118.4  770.55   157.8  767.55   177.5  765.96
   187.4  765.29   197.3  764.34   207.1  763.25   211.5  762.94   217.0  762.56
   226.5  762.85   236.7  763.41   246.6  764.16   256.5  764.50   295.9  764.96
   315.6  765.03   325.5  765.21   345.2  765.22   423.5  764.62   442.5  764.72
   499.6  764.41
#Mann= 3 , 0 , 0
       0     0.1       0   211.5   0.045       0   226.5     0.1       0
Bank Sta=   211.5,   226.5
Exp/Cntr=0.3,0.1

Type RM Length L Ch R = 1 ,248.2,187.8,186.9,185.9
XS GIS Cut Line= 3
     2148042.377      364860.581     2147793.003      364542.210
     2147620.766      364536.801
#Sta/Elev= 30
     9.9  762.59    19.7  762.86    39.5  763.23    59.2  763.45    69.0  763.55
    78.9  763.35    88.8  762.86    98.6  762.23   138.1  759.53   148.0  759.36
   157.8  758.95   207.1  755.57   226.9  753.88   231.6  753.76   236.7  753.63
   246.6  753.76   256.5  753.99   295.9  755.21   305.8  755.35   325.5  755.81
   355.1  755.82   365.0  756.01   404.4  755.75   433.1  756.02   452.3  756.30
   481.0  756.98   500.1  757.68   557.6  758.94   567.2  759.25   576.7  759.44
#Mann= 3 , 0 , 0
       0     0.1       0   231.6   0.045       0   246.6     0.1       0
Bank Sta=   231.6,   246.6
Exp/Cntr=0.3,0.1

Type RM Length L Ch R = 1 ,61.3,55.2,61.3,67.4
XS GIS Cut Line= 5
     2148117.861      364772.640     2148110.401      364648.254
     2148002.033      364515.144     2147888.210      364385.647
     2147653.635      364429.112
#Sta/Elev= 30
     9.6  758.34    28.8  757.56    47.9  757.22   105.4  754.68   115.0  754.46
   153.2  754.48   172.3  753.96   181.8  753.40   191.4  752.27   200.9  750.30
   210.4  748.03   210.6  748.04   225.6  748.72   239.0  749.21   248.6  749.32
   267.6  749.17   296.3  749.53   315.4  749.95   334.6  750.78   344.1  750.98
   372.9  750.99   449.5  750.37   459.1  750.56   468.7  750.49   508.4  751.83
   558.1  752.91   578.0  753.60   617.8  754.06   647.6  754.69   707.2  755.44
#Mann= 3 , 0 , 0
       0     0.1       0   210.6   0.045       0   225.6     0.1       0
Bank Sta=   210.6,   225.6
Exp/Cntr=0.3,0.1